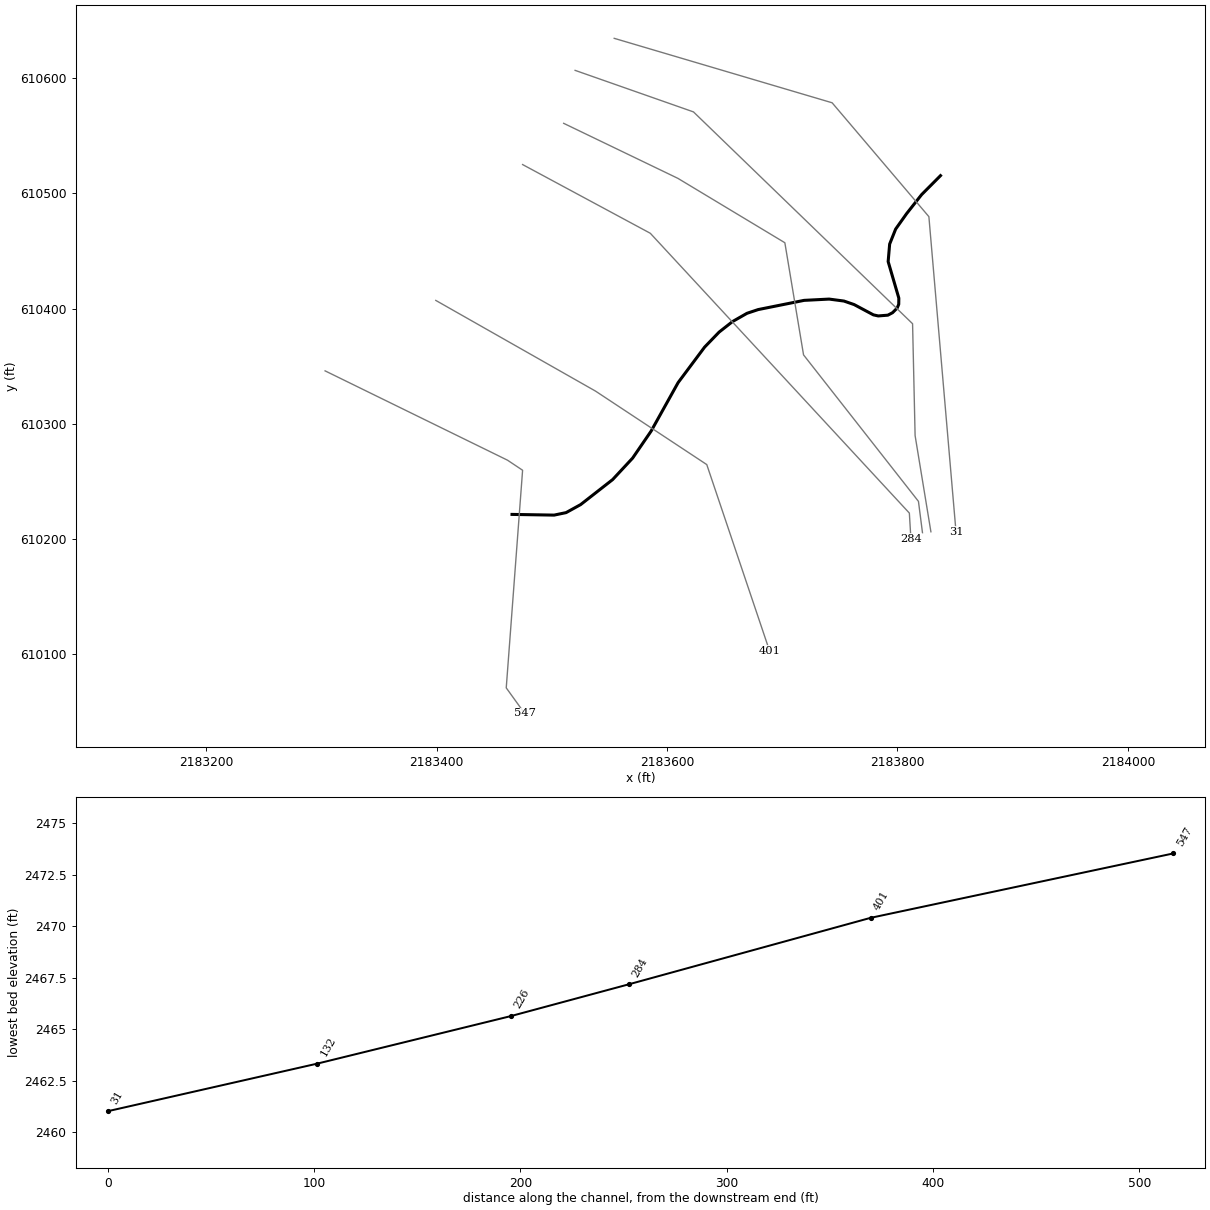
--- MARSHFKT1.prj (project) ---

Proj Title=MARSHFKT1
Current Plan=p01
Default Exp/Contr=0,0
English Units
Geom File=g01
Flow File=f01
Plan File=p01
BEGIN DESCRIPTION:
----------MODEL BY WOOD PLC 2022----------
AFH study
Randolph County, WV
HEC-RAS Version: RAS 6.2
Vertical Datum: NAVD88
Projection: NAD 1983 StatePlane West Virginia S FIPS 4702 (US Feet)
Terrain: 1-meter LIDAR (FEMA Region III 3DEP collected 2016-2018)
Land Use: 2019 NLCD
Hydrologic Method:
WV SIR2010-5033 regression equations
Additional Model Notes:
None
END DESCRIPTION:
DSS Export Rating Curves= 0
DSS Export Rating Curve Sorted= 0
DSS Export Volume Flow Curves= 0
DXF OffsetX= 0
DXF OffsetY= 0
DXF ScaleX= 0
DXF ScaleY= 0

--- MARSHFKT1.p01 (plan) ---

Plan Title=Floodplain
Program Version=6.20
Short Identifier=Floodplain
Geom File=g01
Flow File=f01
Subcritical Flow
K Sum by GR= 0
Std Step Tol= 0.01
Critical Tol= 0.01
Num of Std Step Trials= 20
Max Error Tol= 0.3
Flow Tol Ratio= 0.001
Split Flow NTrial= 30
Split Flow Tol= 0.02
Split Flow Ratio= 0.02
Log Output Level= 0
Friction Slope Method= 1
Unsteady Friction Slope Method= 2
Unsteady Bridges Friction Slope Method= 1
Parabolic Critical Depth
Global Vel Dist= 0 , 0 , 0
Global Log Level= 0
CheckData=False
Encroach Param=-1 ,0,0, 0
Mapping Interval=1HOUR
Computation Time Step Use Courant=        0
Computation Time Step Use Time Series=    0
Computation Time Step Count To Double=0
Computation Time Step Max Doubling=0
Computation Time Step Max Halving=0
Computation Time Step Residence Courant=0
Run HTab= 0
Run UNet= 0
Run Sediment= 0
Run PostProcess= 0
Run WQNet= 0
Run RASMapper= 0
UNET Theta= 0
UNET Theta Warmup= 0
UNET ZTol= 0
UNET ZSATol= 0
UNET MxIter= 0
UNET Max Iter WO Improvement= 0
UNET MaxInSteps= 0
UNET DtIC= 0
UNET DtMin= 0
UNET MaxCRTS= 0
UNET WFStab= 0
UNET SFStab= 0
UNET WFX= 1
UNET SFX= 1
UNET Gravity=32.174
UNET 1D Methodology=Finite Difference
UNET DSS MLevel= 1
UNET Pardiso=0
UNET DZMax Abort= 0
UNET Use Existing IB Tables= 0
UNET Froude Reduction=False
UNET Froude Limit= 0
UNET Froude Power= 0
UNET D1 Cores= 0
UNET WindReference=Eulerian
UNET WindDragFormulation=Hsu (1988)
UNET D2 Coriolis=0
UNET D2 Cores= 0
UNET D2 Theta= 1
UNET D2 Theta Warmup= 1
UNET D2 Z Tol= 0.01
UNET D2 Volume Tol= 0.01
UNET D2 Max Iterations= 20
UNET D2 Equation= 0
UNET D2 RampUpFraction=0.1
UNET D2 TimeSlices= 1
UNET D2 Turbulence Formulation=Non-Conservative (original)
UNET D2 Eddy Viscosity=0.3
UNET D2 Transverse Eddy Viscosity=0.1
UNET D2 Smagorinsky Mixing=0
UNET D2 BCVolumeCheck=0
UNET D2 Cores=0
UNET D2 SolverType=PARDISO (Direct)
UNET D2 Minimum Iterations= 2147483647
UNET D2 Maximum Iterations= 2147483647
UNET D2 Restart Number= 10
UNET D2 Relaxation Coeff=1.3
UNET D2 SOR Precondition Iterations= 10
UNET D2 ILUT Maximum Fill= 8
UNET D2 ILUT Tolerance=1E-08
UNET D1D2 MaxIter= 0
UNET D1D2 ZTol=0.01
UNET D1D2 QTol=0.1
UNET D1D2 MinQTol=1
Write IC File= 0
Write IC File at Fixed DateTime=0
Write IC File at Sim End=0
Echo Input=False
Echo Parameters=False
Echo Output=False
Write Detailed= 0
HDF Write Warmup=0
HDF Write Time Slices=0
HDF Flush=0
HDF Compression= 1
HDF Chunk Size= 1
HDF Spatial Parts= 1
HDF Use Max Rows=0
HDF Fixed Rows= 1
Calibration Method= 0
Calibration Iterations= 20
Calibration Max Change=0.05
Calibration Tolerance=0.2
Calibration Maximum=1.5
Calibration Minimum=0.5
Calibration Optimization Method= 1
WQ AD Non Conservative
WQ ULTIMATE=-1
WQ Max Comp Step=1HOUR
WQ Output Interval=15MIN
WQ Output Selected Increments= 0
WQ Output face flow=0
WQ Output face velocity=0
WQ Output face area=0
WQ Output face dispersion=0
WQ Output cell volume=0
WQ Output cell surface area=0
WQ Output cell continuity=0
WQ Output cumulative cell continuity=0
WQ Output face conc=0
WQ Output face dconc_dx=0
WQ Output face courant=0
WQ Output face peclet=0
WQ Output face adv mass=0
WQ Output face disp mass=0
WQ Output cell mass=0
WQ Output cell source sink temp=0
WQ Output nsm pathways=0
WQ Output nsm derived pathways=0
WQ Create Restart=0
WQ Fixed Restart=0
WQ System Summary=0
WQ Write To DSS=0
Sorting and Armoring Iterations= 10
XS Update Threshold= 0.02
Bed Roughness Predictor= 0
Hydraulics Update Threshold= 0.02
Energy Slope Method= 1
Volume Change Method= 1
Sediment Retention Method= 0
Sediment TS Multiplier= 1
Warm Up Method= 0
XS Weighting Method= 0
Number of US Weighted Cross Sections= 1
Number of DS Weighted Cross Sections= 1
Upstream XS Weight=0
Main XS Weight=1
Downstream XS Weight=0
Number of DS XS's Weighted with US Boundary= 1
Upstream Boundary Weight= 1
Weight of XSs Associated with US Boundary= 0
Number of US XS's Weighted with DS Boundary= 1
Downstream Boundary Weight= 0.5
Weight of XSs Associated with DS Boundary= 0.5
Percentile Method= 0
Sediment Output Level= 3
Mass or Volume Output= 0
Output Increment Type= 1
Profile and TS Output Increment= 1
Transport Output Increment 1
XS Output Flag= 0
XS Output Increment= 10
Read HDF5 Sediment Hotstart= 0
Sediment Hotstart Type= 0
Write Gradation File= 0
Read Gradation Hotstart= 0
Write HDF5 File= 1
Write Binary Output= 1
Write DSS Sediment File= 0
DSS Sediment Output Type= 1
SV Curve= 0
Specific Gage Flag= 0
Subcell Erosion Methods= 0
Subcell Deposition Methods= 0
Advection Scheme= 1
Matrix Solver= 0
Implicit Weighting Factor= 1
Maximum Outer Loop Convergence Iterations= 5
Convergence Maximum Absolute= 0.001
Convergence RMSE= 0.0001
Grain Fractions Max Abs Error= 0.001
Max Subgrid Regions= 1
Max Subgrid Length Scale= 3.402823E+38
Initial Layer Thickness= 3.402823E+38
Min Layer Thickness= 3.402823E+38
Max Layer Thickness= 3.402823E+38
Number of Layers= 5

--- MARSHFKT1.f01 (steady flow) ---

Flow Title=Flow
Program Version=6.20
Number of Profiles= 1
Profile Names=P100yr
River Rch & RM=MARSHFKT1,Main            ,547
297.6403
Boundary for River Rch & Prof#=MARSHFKT1,Main            , 1
Up Type= 0
Dn Type= 3
Dn Slope=0.0243
DSS Import GetInterval= 0
DSS Import GetPeak= 0
DSS Import FillOption= 0

--- MARSHFKT1.g01 (geometry) ---

Geom Title=Geometry
Program Version=6.20

River Reach=MARSHFKT1       ,Main
Reach XY= 30
     2183465.501      610221.447     2183502.046      610220.839
     2183512.463       610223.01      2183525.05      610229.954
     2183552.827      610251.656     2183570.189      610270.319
     2183586.248      610293.756     2183609.685      610335.857
     2183632.688      610366.673     2183645.275      610379.694
     2183656.872      610388.806     2183669.468      610396.004
      2183679.13      610399.225     2183718.983      610407.223
     2183740.761       610408.34     2183753.606      610406.631
     2183762.463      610403.565     2183779.182      610394.641
     2183783.364      610393.712     2183791.732      610394.376
     2183795.796      610396.534     2183799.789      610400.527
     2183801.168      610403.837     2183801.242      610409.181
     2183791.977      610440.891     2183793.279      610456.083
     2183798.487      610469.103     2183808.036      610482.558
     2183821.056      610499.051      2183837.42      610515.484

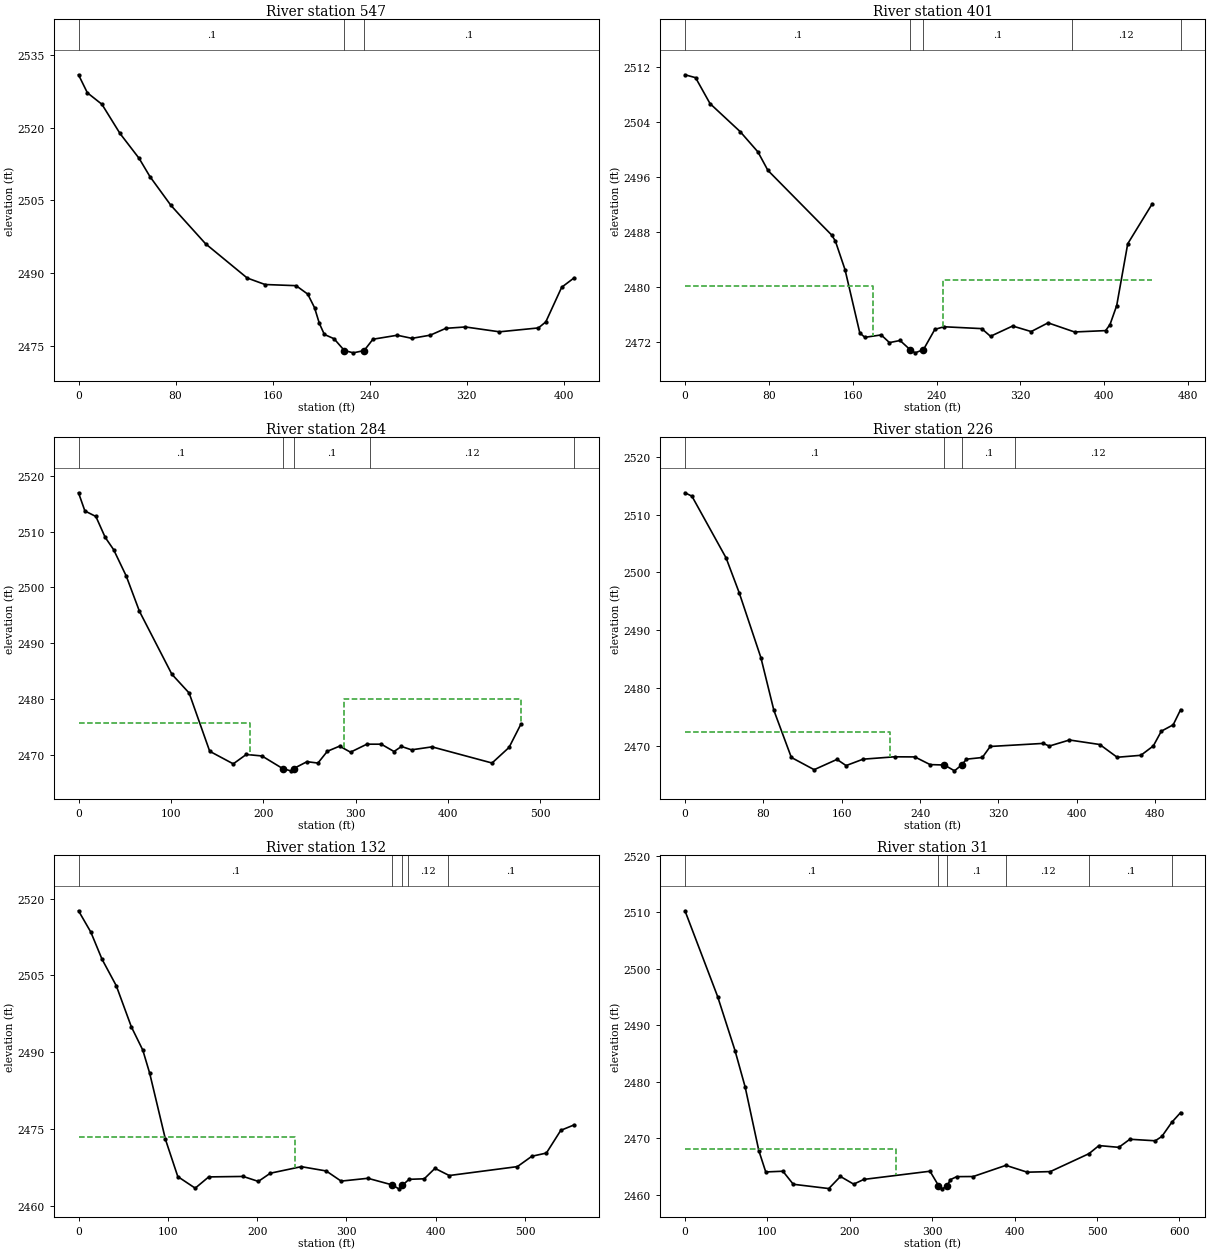
Type RM Length L Ch R = 1 ,547     ,137.4,146.8,153.3
XS GIS Cut Line= 5
2183303.26401145610346.0366891942183461.58690698610268.513064488
2183474.68949143610259.7780081832183460.49502494610070.882415587
2183476.45124088610048.753381576
#Sta/Elev= 30
       0 2530.92     7.3  2527.2    19.3 2524.83    34.2 2518.81      50 2513.66
    58.9 2509.91    76.1    2504   104.8 2496.04   139.1 2488.98   153.8 2487.64
   179.4  2487.4     189 2485.66   194.6 2482.87   198.6 2479.61   202.7 2477.34
   210.7 2476.45   219.2 2474.02   226.6 2473.54   235.5 2474.01   242.8 2476.35
   262.8 2477.17   274.9 2476.53   290.1 2477.19   302.9  2478.6     319 2478.88
   347.1 2477.88   379.2 2478.68   385.3 2479.92   398.4 2487.07   408.7 2489.02
#Mann= 3 ,-1,0
       0      .1       0   219.2    .045       0   235.5      .1       0
Bank Sta=219.2,235.5
XS Rating Curve= 0 ,0
Exp/Cntr(USF)=0,0
Exp/Cntr=0.3,0.1

Type RM Length L Ch R = 1 ,401     ,118.9,116.9,116.2
XS GIS Cut Line= 4
 2183399.3496308610407.182083329  2183537.974227610328.471172748
2183634.55074655610264.6872469872183689.04233599 610103.00318205
#Sta/Elev= 30
       0 2510.93    10.1 2510.51    23.9 2506.73    52.7 2502.64    69.6 2499.69
    79.1    2497     140 2487.57   143.5 2486.69   152.7 2482.53   166.8 2473.31
   171.6 2472.67   187.2 2473.02   195.1  2471.9   205.2 2472.21   214.8 2470.87
   219.6 2470.41   227.52470.877   238.4 2473.83   247.1 2474.21   283.1 2473.94
   291.5 2472.82   312.6 2474.32   330.3 2473.51   346.4 2474.78   371.7 2473.45
   401.3 2473.65   405.5 2474.53   411.9  2477.3   422.4  2486.3   445.8 2492.13
#Mann= 5 ,-1,0
       0      .1       0   214.8    .045       0   227.5      .1       0
  369.41     .12       0  472.89      .1       0
#XS Ineff= 2 , 0
          179.42 2480.16   245.9         2481.08
Permanent Ineff=
       F       F
Bank Sta=214.8,227.5
XS Rating Curve= 0 ,0
Exp/Cntr(USF)=0,0
Exp/Cntr=0.3,0.1

Type RM Length L Ch R = 1 ,284     ,62.3,57.4,55.8
XS GIS Cut Line= 4
2183474.68949143610525.1053434462183585.54311975 610465.45331108
2183810.37696749610222.5996374692183811.72431679 610200.33881337
#Sta/Elev= 30
       0 2516.95     6.9  2513.7    18.8 2512.71    28.9 2508.97      38 2506.78
    51.7 2502.05      66 2495.74   101.1 2484.48   119.8 2481.12   142.1 2470.69
   167.6 2468.44   181.7 2470.12   198.7 2469.85   221.3 2467.58   229.8 2467.19
   232.92467.589   247.5 2468.83   259.3 2468.58   269.5 2470.69   282.8 2471.61
   294.6 2470.53   312.3 2471.96   327.9 2471.96   341.7 2470.65   349.8 2471.55
   360.7 2470.95   382.9 2471.48   447.9 2468.59   466.3 2471.38   479.1 2475.53
#Mann= 5 ,-1,0
       0      .1       0   221.3    .045       0   232.9      .1       0
  315.88     .12       0  536.83      .1       0
#XS Ineff= 2 , 0
          185.79 2475.67  287.08         2480.07
Permanent Ineff=
       F       F
Bank Sta=221.3,232.9
XS Rating Curve= 0 ,0
Exp/Cntr(USF)=0,0
Exp/Cntr=0.3,0.1

Type RM Length L Ch R = 1 ,226     ,92.6,93.9,96.9
XS GIS Cut Line= 6
2183510.35377399610560.8901016672183609.49243164 610513.12329389
2183702.32226562610457.2451413972183718.54495506610359.909004795
2183818.27397574 610232.777422972183821.76717492610205.587674549
#Sta/Elev= 30
       0 2513.79     7.1  2513.2      42  2502.5    55.3 2496.51    77.5 2485.25
    90.8  2476.1   108.6 2467.96   131.9 2465.84   155.2 2467.62   164.5 2466.55
   181.9 2467.66     214 2468.07   234.7 2468.05   250.3 2466.72   264.9 2466.65
   275.2 2465.64   282.6 2466.67   287.4 2467.66   303.6 2467.95   311.7 2469.86
   365.7 2470.39     372 2469.93   392.6 2470.98   423.5  2470.2   441.3 2467.99
   465.5 2468.33   478.2 2469.95   486.4 2472.51   498.5 2473.61   506.1 2476.24
#Mann= 4 ,-1,0
       0      .1       0   264.9    .045       0   282.6      .1       0
  337.07     .12       0
#XS Ineff= 2 , 0
          209.84 2472.35
Permanent Ineff=
       F       F
Bank Sta=264.9,282.6
XS Rating Curve= 0 ,0
Exp/Cntr(USF)=0,0
Exp/Cntr=0.3,0.1

Type RM Length L Ch R = 1 ,132     ,101,101.5,99.7
XS GIS Cut Line= 5
2183520.26763976610606.854388396 2183623.0113395610570.803967432
2183813.17731009610386.9468205182183815.37308265610289.828320455
2183829.09007356610206.357527393
#Sta/Elev= 30
       0 2517.63    13.8 2513.46    26.3 2508.18    42.3 2502.99    59.2 2494.96
      72 2490.42    79.7 2485.91    97.4 2472.97   111.2 2465.72   130.7 2463.46
   145.8 2465.66   184.4 2465.75   201.4 2464.78   214.8 2466.38   249.5 2467.66
   277.4 2466.82   294.1 2464.84   324.1 2465.39   351.3  2464.1   358.7 2463.33
   362.6    2464   370.2 2465.19   387.2 2465.29   399.2 2467.33   415.2 2465.93
   491.5 2467.67   507.7 2469.69     524 2470.32   540.1 2474.75   555.1 2475.82
#Mann= 5 ,-1,0
       0      .1       0   351.3    .045       0   362.6      .1       0
  368.88     .12       0   413.4      .1       0
#XS Ineff= 2 , 0
          242.62 2473.46
Permanent Ineff=
       F       F
Bank Sta=351.3,362.6
XS Rating Curve= 0 ,0
Exp/Cntr(USF)=0,0
Exp/Cntr=0.3,0.1

Type RM Length L Ch R = 1 ,31      ,,,
XS GIS Cut Line= 4
2183554.21174626610634.6586009542183743.34571524610578.723115341
2183827.33259435610479.8871763462183850.86067481610206.475992266
#Sta/Elev= 30
       0 2510.26    39.6 2495.08    60.7 2485.51      73 2479.06    89.6 2467.79
      98 2464.01   118.8 2464.14   131.4 2461.83   174.5 2461.07   188.6 2463.21
   204.7 2461.85     217 2462.69   297.3 2464.14   307.62461.603   312.4 2461.02
   318.1 2461.57   322.1 2462.65   329.7 2463.18   349.7  2463.2   389.4 2465.18
   415.2 2463.97   443.2 2464.07   490.2 2467.25   502.3 2468.68   526.4 2468.37
   539.8  2469.8   570.6 2469.53   578.6 2470.29   590.6 2472.79   601.4 2474.53
#Mann= 6 ,-1,0
       0      .1       0   307.6    .045       0   318.1      .1       0
   389.4     .12       0   490.2      .1       0   590.6     .12       0
#XS Ineff= 2 , 0
          256.28 2468.07
Permanent Ineff=
       F       F
Bank Sta=307.6,318.1
XS Rating Curve= 0 ,0
Exp/Cntr(USF)=0,0
Exp/Cntr=0.3,0.1
LCMann Table=0

Chan Stop Cuts=-1
Use User Specified Reach Order=0
Composite Channel Slope=5